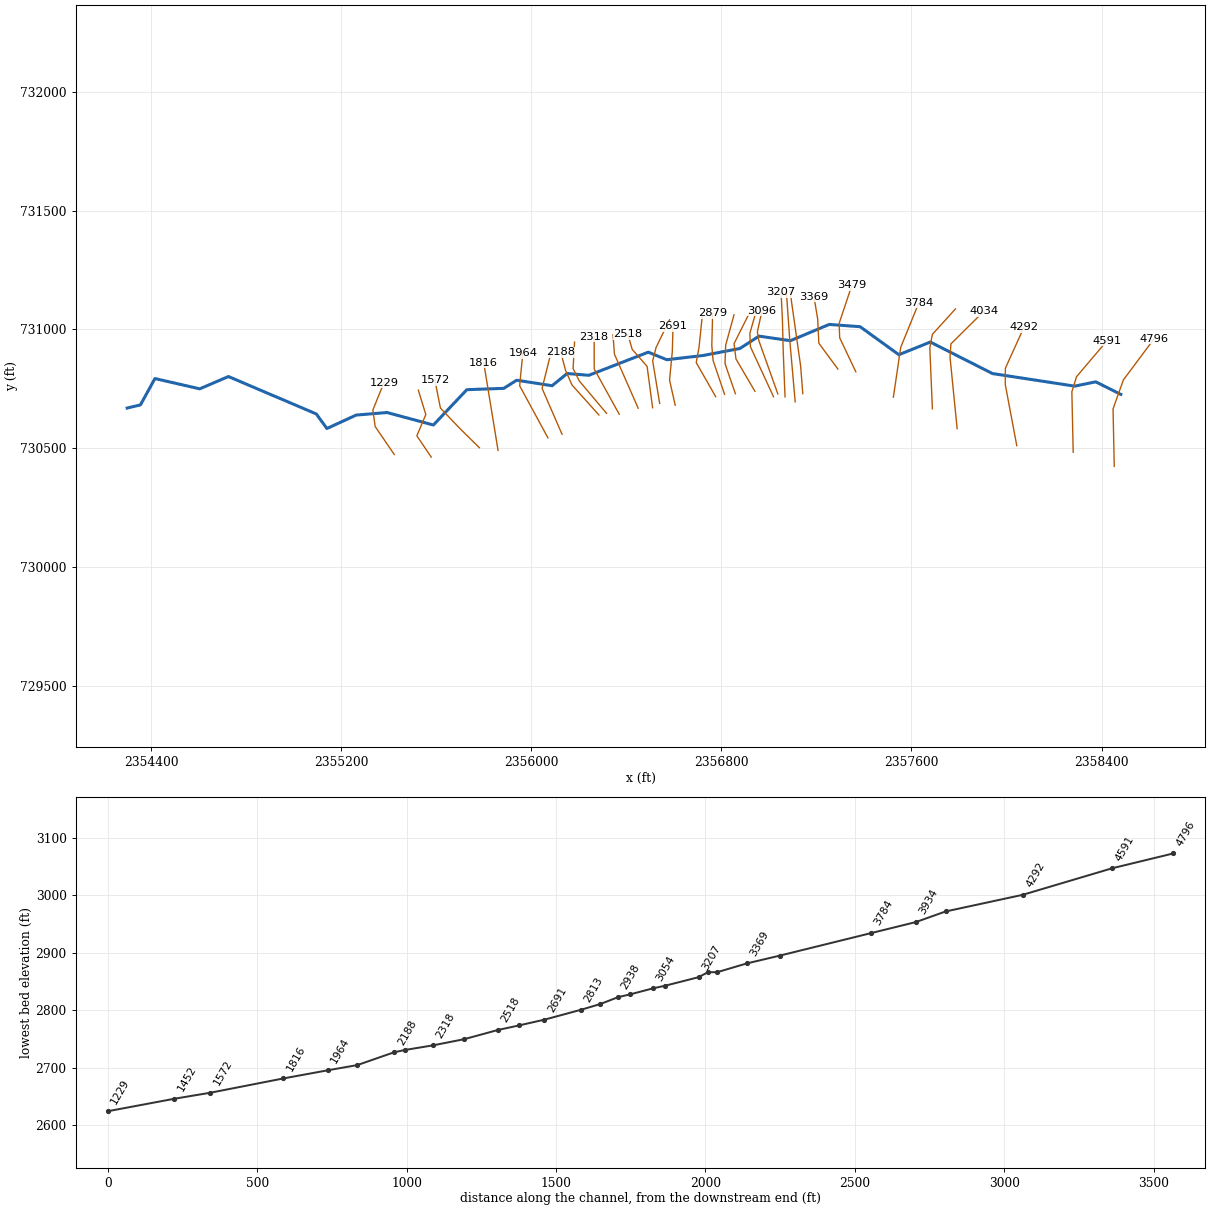
--- PSSNCMPRN.prj (project) ---

Proj Title=PSSNCMPRN
Current Plan=p01
Default Exp/Contr=0,0
English Units
Geom File=g01
Flow File=f01
Plan File=p01
BEGIN DESCRIPTION:
----------MODEL BY WOOD PLC 2022----------
AFH study:PSSNCMPRN
Randolph County, WV
HEC-RAS Version: RAS 6.2
Vertical Datum: NAVD88
Projection: NAD 1983 StatePlane West Virginia S FIPS 4702 (US Feet)
Terrain: 1-meter LIDAR (FEMA Region III 3DEP collected 2016-2018)
Land Use: 2019 NLCD
Hydrologic Method:
WV SIR2010-5033 regression equations
Additional Model Notes:
None
END DESCRIPTION:
DSS Export Rating Curves= 0
DSS Export Rating Curve Sorted= 0
DSS Export Volume Flow Curves= 0
DXF OffsetX= 0
DXF OffsetY= 0
DXF ScaleX= 0
DXF ScaleY= 0

--- PSSNCMPRN.p01 (plan) ---

Plan Title=Floodplain
Program Version=6.20
Short Identifier=Floodplain
Geom File=g01
Flow File=f01
Subcritical Flow
K Sum by GR= 0
Std Step Tol= 0.01
Critical Tol= 0.01
Num of Std Step Trials= 20
Max Error Tol= 0.3
Flow Tol Ratio= 0.001
Split Flow NTrial= 30
Split Flow Tol= 0.02
Split Flow Ratio= 0.02
Log Output Level= 0
Friction Slope Method= 1
Unsteady Friction Slope Method= 2
Unsteady Bridges Friction Slope Method= 1
Parabolic Critical Depth
Global Vel Dist= 0 , 0 , 0
Global Log Level= 0
CheckData=True
Encroach Param=-1 ,0,0, 0
Mapping Interval=1HOUR
Computation Time Step Use Courant=        0
Computation Time Step Use Time Series=    0
Computation Time Step Count To Double=0
Computation Time Step Max Doubling=0
Computation Time Step Max Halving=0
Computation Time Step Residence Courant=0
Run HTab= 0
Run UNet= 0
Run Sediment= 0
Run PostProcess= 0
Run WQNet= 0
Run RASMapper=-1
UNET Theta= 0
UNET Theta Warmup= 0
UNET ZTol= 0
UNET ZSATol= 0
UNET MxIter= 0
UNET Max Iter WO Improvement= 0
UNET MaxInSteps= 0
UNET DtIC= 0
UNET DtMin= 0
UNET MaxCRTS= 0
UNET WFStab= 0
UNET SFStab= 0
UNET WFX= 1
UNET SFX= 1
UNET Gravity=32.174
UNET 1D Methodology=Finite Difference
UNET DSS MLevel= 1
UNET Pardiso=0
UNET DZMax Abort= 0
UNET Use Existing IB Tables= 0
UNET Froude Reduction=False
UNET Froude Limit= 0
UNET Froude Power= 0
UNET D1 Cores= 0
UNET WindReference=Eulerian
UNET WindDragFormulation=Hsu (1988)
UNET D2 Coriolis=0
UNET D2 Cores= 0
UNET D2 Theta= 1
UNET D2 Theta Warmup= 1
UNET D2 Z Tol= 0.01
UNET D2 Volume Tol= 0.01
UNET D2 Max Iterations= 20
UNET D2 Equation= 0
UNET D2 RampUpFraction=0.1
UNET D2 TimeSlices= 1
UNET D2 Turbulence Formulation=Non-Conservative (original)
UNET D2 Eddy Viscosity=0.3
UNET D2 Transverse Eddy Viscosity=0.1
UNET D2 Smagorinsky Mixing=0
UNET D2 BCVolumeCheck=0
UNET D2 Cores=0
UNET D2 SolverType=PARDISO (Direct)
UNET D2 Minimum Iterations= 2147483647
UNET D2 Maximum Iterations= 2147483647
UNET D2 Restart Number= 10
UNET D2 Relaxation Coeff=1.3
UNET D2 SOR Precondition Iterations= 10
UNET D2 ILUT Maximum Fill= 8
UNET D2 ILUT Tolerance=1E-08
UNET D1D2 MaxIter= 0
UNET D1D2 ZTol=0.01
UNET D1D2 QTol=0.1
UNET D1D2 MinQTol=1
Write IC File= 0
Write IC File at Fixed DateTime=0
Write IC File at Sim End=0
Echo Input=False
Echo Parameters=False
Echo Output=False
Write Detailed= 0
HDF Write Warmup=0
HDF Write Time Slices=0
HDF Flush=0
HDF Compression= 1
HDF Chunk Size= 1
HDF Spatial Parts= 1
HDF Use Max Rows=0
HDF Fixed Rows= 1
Calibration Method= 0
Calibration Iterations= 20
Calibration Max Change=0.05
Calibration Tolerance=0.2
Calibration Maximum=1.5
Calibration Minimum=0.5
Calibration Optimization Method= 1
WQ AD Non Conservative
WQ ULTIMATE=-1
WQ Max Comp Step=1HOUR
WQ Output Interval=15MIN
WQ Output Selected Increments= 0
WQ Output face flow=0
WQ Output face velocity=0
WQ Output face area=0
WQ Output face dispersion=0
WQ Output cell volume=0
WQ Output cell surface area=0
WQ Output cell continuity=0
WQ Output cumulative cell continuity=0
WQ Output face conc=0
WQ Output face dconc_dx=0
WQ Output face courant=0
WQ Output face peclet=0
WQ Output face adv mass=0
WQ Output face disp mass=0
WQ Output cell mass=0
WQ Output cell source sink temp=0
WQ Output nsm pathways=0
WQ Output nsm derived pathways=0
WQ Create Restart=0
WQ Fixed Restart=0
WQ System Summary=0
WQ Write To DSS=0
Sorting and Armoring Iterations= 10
XS Update Threshold= 0.02
Bed Roughness Predictor= 0
Hydraulics Update Threshold= 0.02
Energy Slope Method= 1
Volume Change Method= 1
Sediment Retention Method= 0
Sediment TS Multiplier= 1
Warm Up Method= 0
XS Weighting Method= 0
Number of US Weighted Cross Sections= 1
Number of DS Weighted Cross Sections= 1
Upstream XS Weight=0
Main XS Weight=1
Downstream XS Weight=0
Number of DS XS's Weighted with US Boundary= 1
Upstream Boundary Weight= 1
Weight of XSs Associated with US Boundary= 0
Number of US XS's Weighted with DS Boundary= 1
Downstream Boundary Weight= 0.5
Weight of XSs Associated with DS Boundary= 0.5
Percentile Method= 0
Sediment Output Level= 3
Mass or Volume Output= 0
Output Increment Type= 1
Profile and TS Output Increment= 1
Transport Output Increment 1
XS Output Flag= 0
XS Output Increment= 10
Read HDF5 Sediment Hotstart= 0
Sediment Hotstart Type= 0
Write Gradation File= 0
Read Gradation Hotstart= 0
Write HDF5 File= 1
Write Binary Output= 1
Write DSS Sediment File= 0
DSS Sediment Output Type= 1
SV Curve= 0
Specific Gage Flag= 0
Subcell Erosion Methods= 0
Subcell Deposition Methods= 0
Advection Scheme= 1
Matrix Solver= 0
Implicit Weighting Factor= 1
Maximum Outer Loop Convergence Iterations= 5
Convergence Maximum Absolute= 0.001
Convergence RMSE= 0.0001
Grain Fractions Max Abs Error= 0.001
Max Subgrid Regions= 1
Max Subgrid Length Scale= 3.402823E+38
Initial Layer Thickness= 3.402823E+38
Min Layer Thickness= 3.402823E+38
Max Layer Thickness= 3.402823E+38
Number of Layers= 5

--- PSSNCMPRN.f01 (steady flow) ---

Flow Title=Flow
Program Version=6.20
Number of Profiles= 1
Profile Names=P100yr
River Rch & RM=PSSNCMPRN,Main,4796
     437
Boundary for River Rch & Prof#=PSSNCMPRN,Main            , 1
Up Type= 0
Dn Type= 3
Dn Slope=0.06612
DSS Import GetInterval= 0
DSS Import GetPeak= 0
DSS Import FillOption= 0

--- PSSNCMPRN.g01 (geometry) ---

Geom Title=Geometry
Program Version=6.20

River Reach=PSSNCMPRN       ,Main
Reach XY= 30
2358481.23100004730726.2890000052358375.32900001730779.067000002
2358286.92299998730760.9810000062357940.99000002730813.894999996
2357679.17300001730946.5269999952357547.03288167730893.159602296
2357383.75800002731011.1219999942357253.78018665731020.660532556
2357090.36543958730952.2066962032356958.23997101730971.472147152
2356877.89894152730919.4144392672356722.54562428730889.901408024
2356570.06162953730872.1389355182356492.28194231730903.949969929
2356241.90800001730806.5840000062356150.64642515730814.128921098
     2356087.395730762.7469999942355938.15442079730785.883545393
2355884.00879511730751.6375941042355728.52002395730746.013032136
2355587.82899998730597.383000001     2355392.516730649.900000006
2355262.49139097730639.1124989462355139.52622032730582.550280866
2355094.75399998730643.9950000052354724.98100001730801.376000002
2354604.26599999730749.5540000052354415.59600005730792.944000006
     2354354.756730682.018000007     2354298.695      730668.663

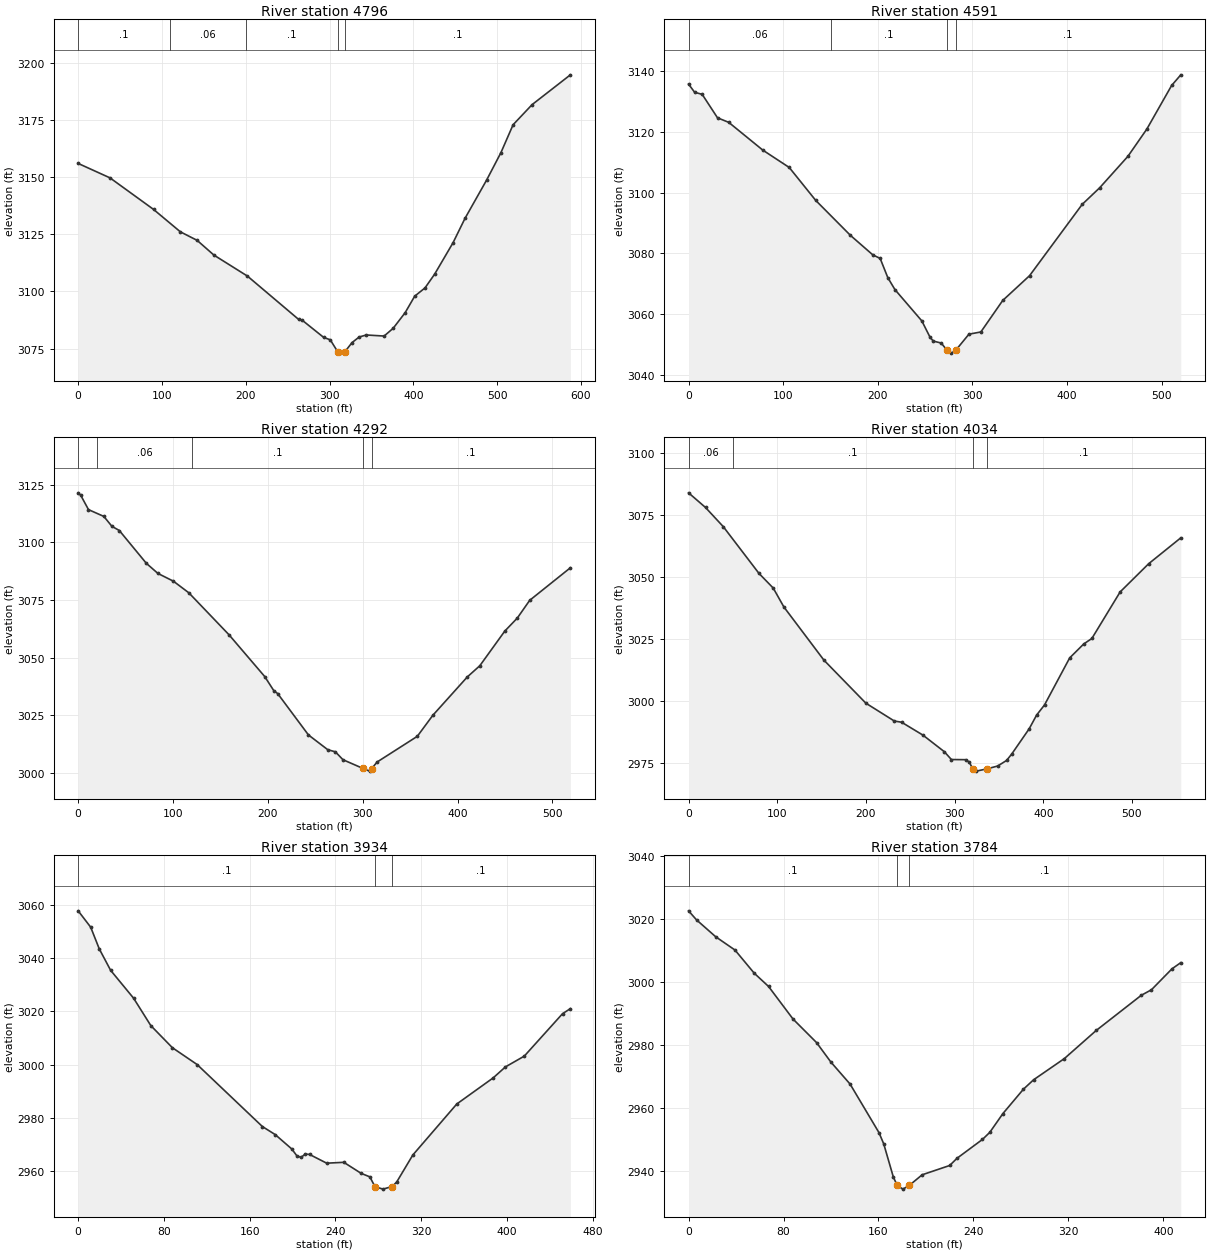
Type RM Length L Ch R = 1 ,4796    ,205.4,205,205.7
XS GIS Cut Line= 4
2358453.40747236730423.2255697552358448.40074313730665.227437831
 2358491.9309026730787.1577706922358621.04894967730960.297483013
#Sta/Elev= 30
       0 3156.01      38 3149.69      90 3135.88     122 3126.07     142 3122.34
     162  3115.9     202 3106.71   263.2 3087.72   267.5 3087.36     293 3079.87
   300.9 3078.81  309.63 3073.67   312.8 3072.98   318.5 3073.66   326.9 3077.59
   335.4 3080.04   343.9 3080.92   365.2 3080.46     376 3083.86   390.3  3090.7
   401.7 3097.92     414 3101.53   425.5 3107.56   447.5 3121.34   461.7 3131.96
   487.5 3148.72   504.6 3160.74   519.1 3172.94   541.8 3181.75   587.5 3194.79
#Mann= 5 ,-1,0
       0      .1       0     110     .06       0     200      .1       0
  309.63    .045       0   318.5      .1       0
Bank Sta=309.63,318.5
XS Rating Curve= 0 ,0
Exp/Cntr=0.3,0.1

Type RM Length L Ch R = 1 ,4591    ,297.2,299.5,300.1
XS GIS Cut Line= 4
2358280.62836122730482.7724315022358275.04132308730736.816957875
 2358294.6575223730800.7642246092358423.67788668730952.565013545
#Sta/Elev= 30
       0 3135.71     6.4 3133.01    14.4 3132.33    30.6  3124.6    42.4 3123.12
    78.4 3113.98   106.4 3108.25   134.4  3097.4   171.1 3085.88   194.6  3079.5
   202.5 3078.28   210.6 3071.94   218.1 3068.03   246.5 3057.73   255.3 3052.28
   258.7 3051.07     267 3050.43273.18873048.054   277.7 3047.11   282.3 3048.03
   296.3 3053.35   308.9 3054.08     332 3064.45   360.4 3072.62     416  3096.1
   434.5 3101.57   464.3 3111.92   484.3 3120.89   510.5 3135.25   520.2 3138.76
#Mann= 4 ,-1,0
       0     .06       0     150      .1       0273.1887    .045       0
   282.3      .1       0
Bank Sta=273.1887,282.3
XS Rating Curve= 0 ,0
Exp/Cntr(USF)=0,0
Exp/Cntr=0.3,0.1

Type RM Length L Ch R = 1 ,4292    ,257.6,258.1,259.6
XS GIS Cut Line= 4
2358043.11192764  730510.50766782357994.66489663730768.401541205
2357995.21913672730836.2579378412358072.96769156 731008.21938196
#Sta/Elev= 30
       0 3121.47     2.7 3120.42    10.9 3114.19    27.1 3111.24    35.6 3106.95
    43.4 3105.14    71.9 3090.92    84.1 3086.53   100.4 3083.18   116.7 3078.13
     159 3059.97   196.7 3041.84   206.2 3035.77   210.4 3034.44   242.8 3016.53
   263.2 3010.12   271.2 3009.21   279.2 3005.79   300.4 3001.99   307.2 3000.84
  309.46 3001.93   315.2 3004.79   357.6 3015.93     374 3025.06   410.3 3041.66
   423.5 3046.52   449.8 3061.52     463 3067.17   476.1 3074.88     519 3088.99
#Mann= 5 ,-1,0
       0      .1       0      20     .06       0     120      .1       0
   300.4    .045       0  309.46      .1       0
Bank Sta=300.4,309.46
XS Rating Curve= 0 ,0
Exp/Cntr=0.3,0.1

Type RM Length L Ch R = 1 ,4034    ,99.1,99.7,95.1
XS GIS Cut Line= 4
2357792.17407773730582.1934727532357762.17809688730883.552753474
2357765.93903728730938.6248305062357905.85575733731077.359176272
#Sta/Elev= 30
       0 3083.94    19.1 3078.04    39.2 3070.29    79.4 3051.48    95.5 3045.56
   107.5 3037.95   152.6 3016.55     200 2999.18   232.1 2991.99   240.2 2991.53
   264.3 2986.33   288.4 2979.65   296.4 2976.49   312.5 2976.43   316.5 2975.47
   320.5 2972.76   324.5 2971.82   336.6 2972.74   348.6 2973.88   358.6 2976.12
   364.3 2978.64   384.1 2988.87   392.5  2994.4   401.4 2998.48   429.8 3017.44
   445.7 3023.07   454.8 3025.26   486.7 3044.02   518.9 3055.39   555.1 3065.81
#Mann= 4 ,-1,0
       0     .06       0      50      .1       0   320.5    .045       0
   336.6      .1       0
Bank Sta=320.5,336.6
XS Rating Curve= 0 ,0
Exp/Cntr(USF)=0,0
Exp/Cntr=0.3,0.1

Type RM Length L Ch R = 1 ,3934    ,149.5,149.7,153.8
XS GIS Cut Line= 4
2357688.01154873730665.4652265582357677.12644752730922.789019034
2357688.01154873 730978.956141252357785.10665147731086.065537103
#Sta/Elev= 30
       0 3057.77    11.7 3051.63    19.7 3043.49    30.3 3035.45    51.8 3024.94
    67.8  3014.7    87.9 3006.41     111 3000.09   171.9 2976.82   183.9 2973.79
   199.3 2968.41   203.9 2965.93   207.9 2965.22   211.9 2966.48   215.9 2966.35
   231.9 2963.07   247.9 2963.39   264.1 2959.24   272.2 2957.93   276.9 2954.28
   284.4 2953.33   292.9  2954.3   297.2 2955.98   312.3 2966.15   353.3 2985.28
   387.3 2995.09   398.7  2999.2   416.3 3003.25     452 3019.18   459.3 3021.06
#Mann= 3 ,-1,0
       0      .1       0   276.9    .045       0   292.9      .1       0
Bank Sta=276.9,292.9
XS Rating Curve= 0 ,0
Exp/Cntr(USF)=0,0
Exp/Cntr=0.3,0.1

Type RM Length L Ch R = 1 ,3784    ,298.2,305.5,304.8
XS GIS Cut Line= 3
2357523.79505566730714.5094921172357554.61828953730924.062133621
2357631.02438861 731112.05852766
#Sta/Elev= 30
       0 3022.45     6.7 3019.58    22.9 3014.21    39.1 3010.01    55.3 3002.67
    67.4 2998.45      88 2988.12   107.8 2980.66   119.9 2974.47   136.1 2967.47
   160.4 2952.09   164.4 2948.53   172.5 2938.01  175.71 2935.36   180.6 2934.15
     186 2935.34   196.8  2938.7     220 2941.65   226.1 2943.92   247.6 2949.92
   253.8 2952.17   264.8 2958.11   282.1 2965.85   290.7 2968.85   316.6 2975.57
   343.4 2984.48   381.4 2995.65     390 2997.41   407.3 3004.06   414.7 3006.01
#Mann= 3 ,-1,0
       0      .1       0  175.71    .045       0     186      .1       0
Bank Sta=175.71,186
XS Rating Curve= 0 ,0
Exp/Cntr=0.3,0.1

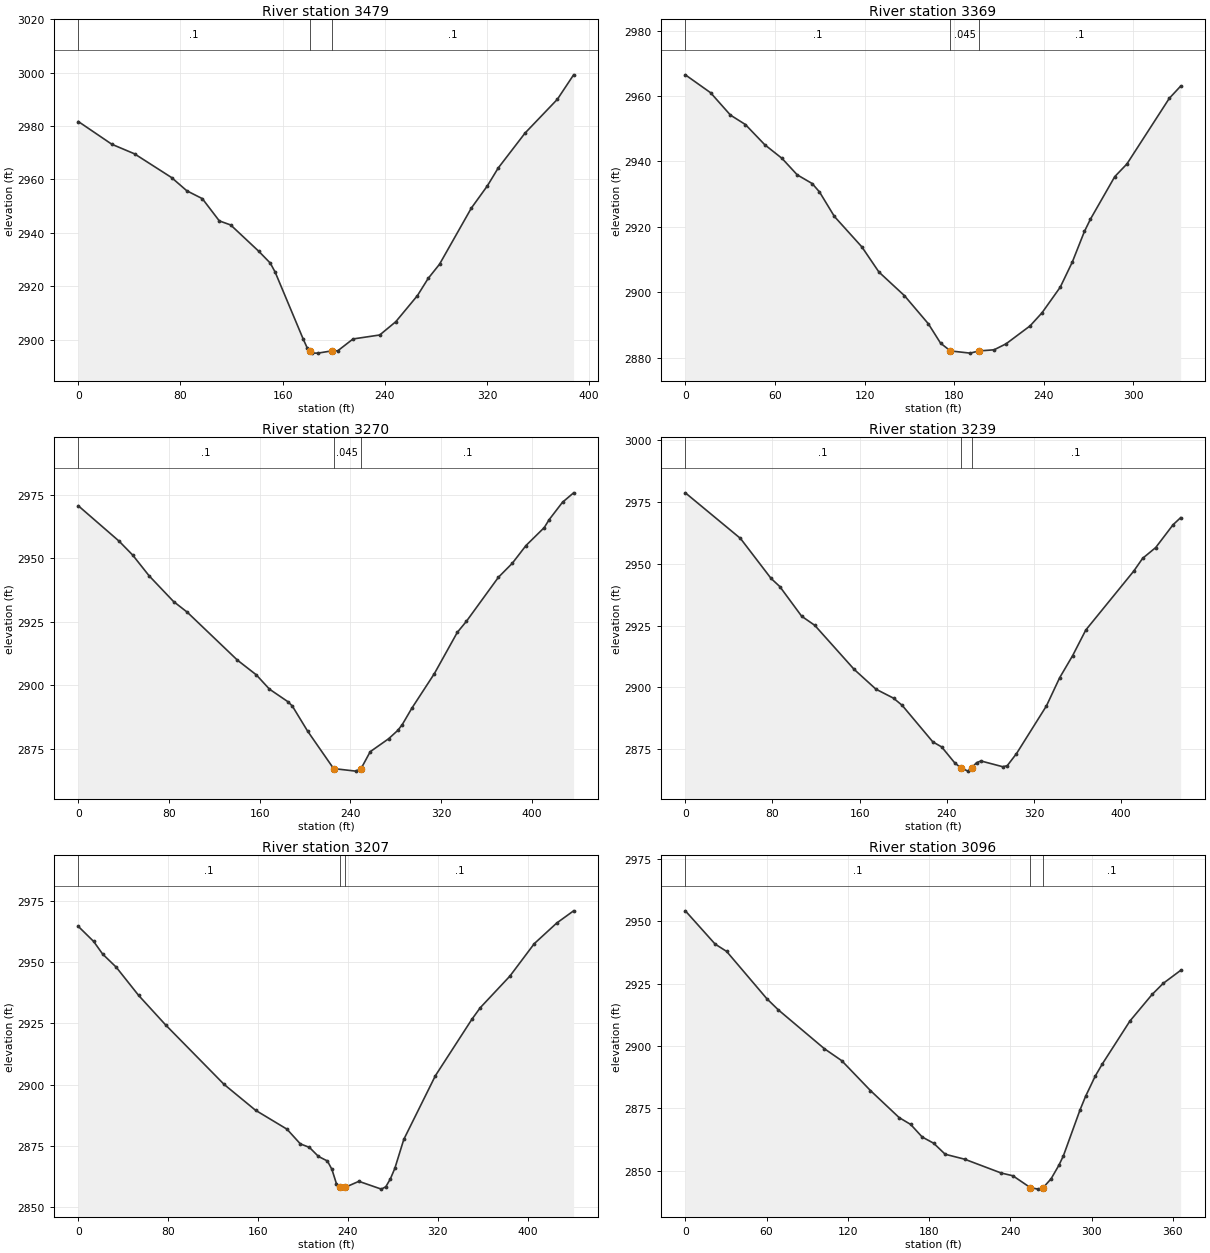
Type RM Length L Ch R = 1 ,3479    ,103.6,109.8,107.5
XS GIS Cut Line= 4
2357365.65299348730821.4261139842357297.74209368730964.537732684
2357295.56507344731025.0588953812357349.03820487731185.243063089
#Sta/Elev= 30
       0 2981.73    26.3 2973.19      44 2969.62      73 2960.73      85 2955.75
    97.1 2952.82   110.4 2944.48   119.3 2942.95   141.4 2933.04   150.3 2928.66
   154.1  2925.3     176 2900.27   179.1 2896.99  181.39 2895.82   183.1 2894.92
   187.6 2894.91     199  2895.8   203.1 2895.77   215.1 2900.22     236 2901.71
   248.6  2906.7   265.5 2916.46   273.9  2922.9   282.8 2928.22   307.7 2949.26
   320.3 2957.63   328.7 2964.26   349.8 2977.41   375.1 2990.07   387.8 2999.23
#Mann= 3 ,-1,0
       0      .1       0  181.39    .045       0     199      .1       0
Bank Sta=181.39,199
XS Rating Curve= 0 ,0
Exp/Cntr(USF)=0,0
Exp/Cntr=0.3,0.1

Type RM Length L Ch R = 1 ,3369    ,97,99.1,97.5
XS GIS Cut Line= 4
2357290.21427057730832.822831428 2357210.0999257730941.673843474
2357205.31048117731043.1229867012357189.63593544 731136.73485706
#Sta/Elev= 30
       0 2966.48    16.9 2961.01    30.2 2954.17    40.2 2951.29    53.2  2945.1
    64.7 2940.95    74.9 2935.91    84.9 2933.25    89.8 2930.69    99.8 2923.18
   118.2 2913.87   129.6  2906.2   146.7 2898.97   162.7 2890.37   170.9 2884.44
  177.49 2882.08   190.7 2881.41   196.42882.062   206.7 2882.43   214.7 2884.25
   230.8 2889.74   238.8 2893.75     251 2901.58   259.1 2909.29   267.2 2918.63
   271.2 2922.36   287.5 2935.37   295.6 2939.22     324  2959.3   331.6 2963.03
#Mann= 3 ,-1,0
       0      .1       0  177.49    .045       0   196.4      .1       0
Bank Sta=177.49,196.4
XS Rating Curve= 0 ,0
Exp/Cntr(USF)=0,0
Exp/Cntr=0.3,0.1

Type RM Length L Ch R = 1 ,3270    ,30.6,31.2,34.2
XS GIS Cut Line= 4
2357142.48141056730729.4006986952357133.34793046730846.055634339
2357094.84179638731118.2003387082357089.12443849731162.906466861
#Sta/Elev= 30
       0 2970.63    35.9 2956.73    47.9 2951.25    62.5 2943.03      84 2932.93
    96.1 2928.72   140.4 2909.82     157 2904.05   168.6 2898.42   184.8  2893.5
   188.8 2891.76   202.2 2881.93   225.2 2867.13   244.7 2866.13   249.4 2867.12
   257.5 2873.79   273.7 2878.87   281.8 2882.17   285.8 2884.49   294.2 2890.91
   314.1 2904.55   334.3 2920.77   342.4 2925.16   370.6 2942.49   382.8 2947.98
   394.9 2954.98     411 2962.04   415.3 2965.15   427.1 2972.02   436.9 2975.73
#Mann= 3 ,-1,0
       0      .1       0   225.2    .045       0   249.4      .1       0
Bank Sta=225.2,249.4
XS Rating Curve= 0 ,0
Exp/Cntr=0.3,0.1

Type RM Length L Ch R = 1 ,3239    ,31.1,31.6,31
XS GIS Cut Line= 3
2357110.47796393730694.8025840912357087.63667281 730955.33606088
2357074.07465621 731148.05945467
#Sta/Elev= 30
       0 2978.75    50.6 2960.28    78.7 2944.08    86.7  2940.8   106.8 2928.77
   118.8  2925.1     155 2907.24     175 2899.23   191.1  2895.6   199.1 2892.67
   227.2 2877.89   235.3 2875.85   247.3  2869.4  252.69 2867.46   259.4 2866.05
   262.8 2867.44   267.4 2869.48   271.4 2870.16   291.4 2867.83   295.5 2868.25
     304 2873.14   331.5 2892.47   343.6 2903.85   355.6 2912.87   367.6 2923.18
   411.7 2947.09   419.8 2952.22   431.8 2956.59   447.8 2965.86   454.7  2968.7
#Mann= 3 ,-1,0
       0      .1       0  252.69    .045       0   262.8      .1       0
Bank Sta=252.69,262.8
XS Rating Curve= 0 ,0
Exp/Cntr(USF)=0,0
Exp/Cntr=0.3,0.1

Type RM Length L Ch R = 1 ,3207    ,110.5,110.8,112.1
XS GIS Cut Line= 4
 2357067.7826761730715.5133643972357060.32529994730903.274246717
 2357056.6828278731043.769600789  2357050.958943731156.165884047
#Sta/Elev= 30
       0 2964.55    13.7 2958.39    21.7 2953.24    33.7 2947.94    53.7  2936.4
    77.7 2924.37   129.8 2900.08   157.8 2889.53   185.8 2881.81   197.7 2875.81
   205.8 2874.37   213.8  2870.7   221.8 2868.82   225.8 2865.42   229.8  2859.6
  232.62 2858.16   237.8 2858.12   249.8 2860.53   269.8 2857.35   273.8 2858.33
   277.8 2861.49   281.8 2865.79   289.8 2877.64   317.9  2903.6   350.5  2926.7
   357.9 2931.38   384.3 2944.28     406 2957.52     426 2965.93     441  2970.9
#Mann= 3 ,-1,0
       0      .1       0  232.62    .045       0   237.8      .1       0
Bank Sta=232.62,237.8
XS Rating Curve= 0 ,0
Exp/Cntr(USF)=0,0
Exp/Cntr=0.3,0.1

Type RM Length L Ch R = 1 ,3096    ,48.8,42,40.3
XS GIS Cut Line= 4
2357037.48952726730728.4336505182356957.59489991730952.353976422
2356951.28828368730989.424636842 2356970.7545725731077.718636701
#Sta/Elev= 30
       0 2954.18      22 2940.85    30.5 2937.91    60.2 2918.95    68.7 2914.47
   102.7 2898.91   115.5 2894.12   136.7 2882.15   157.9 2871.31   166.4 2868.57
   174.9 2863.54   183.4 2861.03   191.9 2856.62   206.3 2854.63   233.2 2849.11
   241.9 2847.99   254.8 2843.24   260.5 2842.64  264.27 2843.24   270.1 2846.77
   275.9 2852.23   279.2 2855.99   291.5 2874.41   295.6 2879.84   302.7 2887.92
   307.9 2892.76   328.3 2909.99   344.7 2920.65   352.9  2925.1   365.8 2930.32
#Mann= 3 ,-1,0
       0      .1       0   254.8    .045       0  264.27      .1       0
Bank Sta=254.8,264.27
XS Rating Curve= 0 ,0
Exp/Cntr(USF)=0,0
Exp/Cntr=0.3,0.1

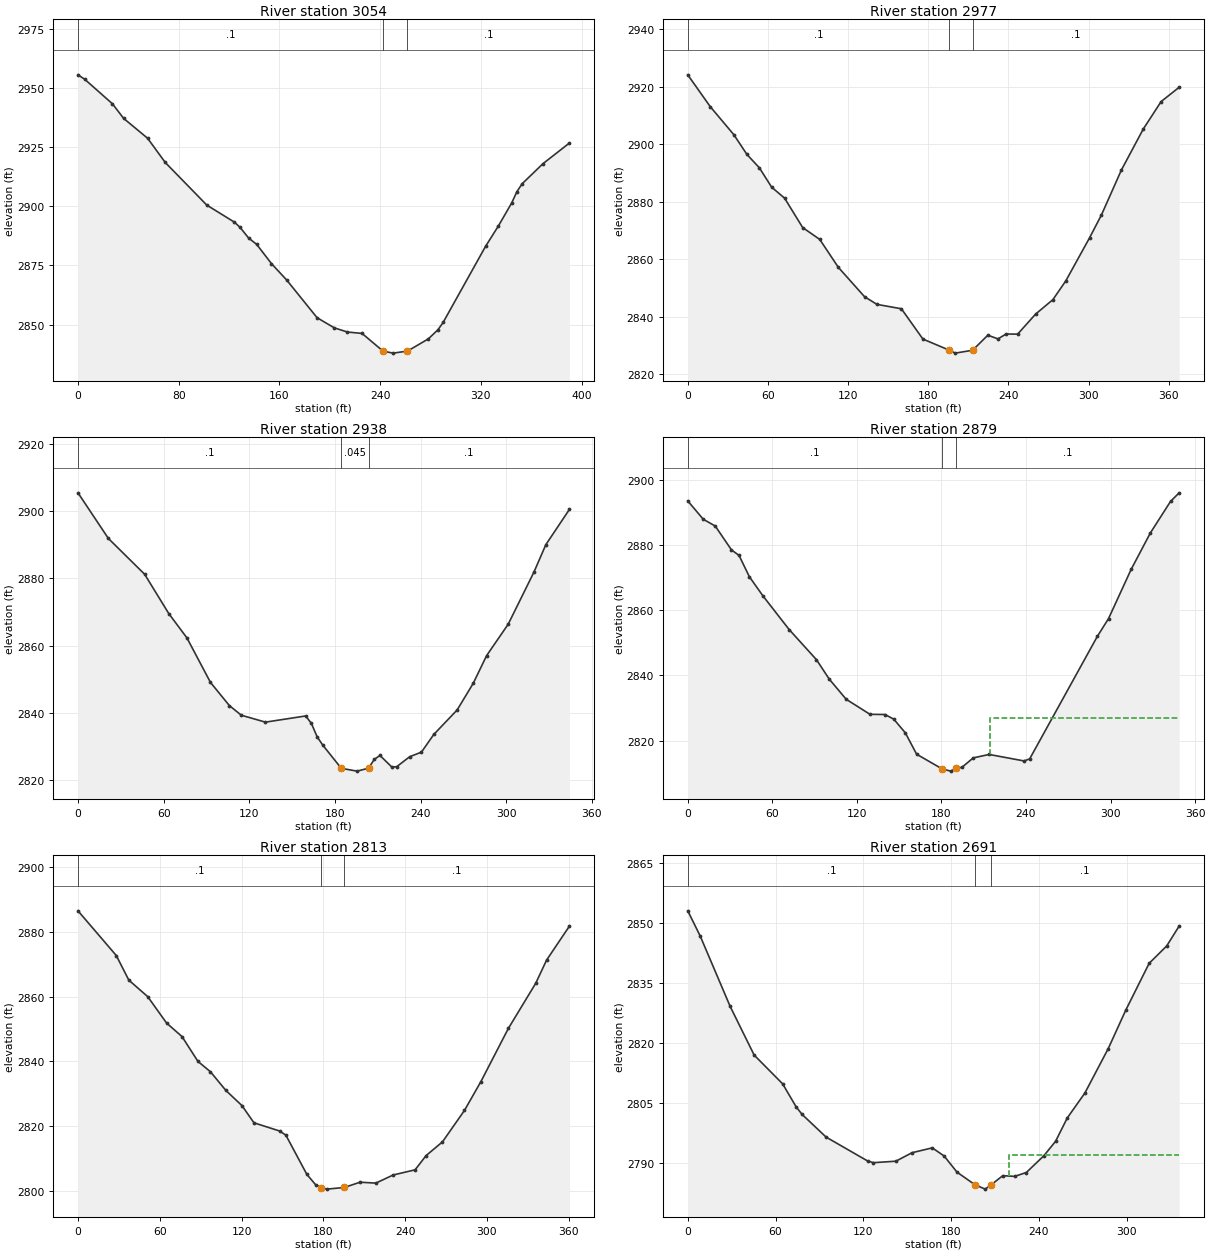
Type RM Length L Ch R = 1 ,3054    ,72.1,76.8,73.5
XS GIS Cut Line= 4
2357019.36486703730716.3439669312356921.95582161730927.136810532
2356919.68511702 730983.047146652356947.66616771731081.280175538
#Sta/Elev= 30
       0 2955.62     5.3 2953.76    27.4 2943.35    36.2 2937.22    55.3 2928.79
    69.3 2918.55   102.3 2900.52   124.3 2893.28   128.7 2891.11   135.6 2886.54
   141.9 2883.92   153.7 2875.75   165.8  2868.8   189.9 2852.88   203.6 2848.59
     214 2846.82   225.6 2846.24   242.3 2838.75   250.3  2837.9   261.7 2838.76
   278.2  2843.9   285.9 2847.77     290 2850.87   323.7 2883.04   333.8 2891.59
   344.5 2901.44   348.6 2906.17   352.8 2909.56   369.4 2918.08   390.3 2926.76
#Mann= 3 ,-1,0
       0      .1       0   242.3    .045       0   261.7      .1       0
Bank Sta=242.3,261.7
XS Rating Curve= 0 ,0
Exp/Cntr(USF)=0,0
Exp/Cntr=0.3,0.1

Type RM Length L Ch R = 1 ,2977    ,40.3,39.2,37.2
XS GIS Cut Line= 4
2356941.10350339730738.9555246712356861.20476611730875.540751604
2356853.10007258730939.6103297642356918.07535868731069.258819702
#Sta/Elev= 30
       0 2924.08    16.9 2912.98    34.5 2903.27    44.3  2896.4    53.6 2891.76
    62.8 2885.03    72.5  2881.2      86    2871    98.8 2866.87   112.7 2857.17
   132.3 2846.97   141.6 2844.29   159.9 2842.77     176 2832.24   195.82828.357
   200.2 2827.35  213.19 2828.35   224.6 2833.58   232.2  2832.3   238.2 2833.99
   246.9 2833.95   260.4 2840.94   273.3 2845.95   282.9 2852.42   300.8 2867.48
   309.6 2875.35   324.6 2891.03   340.9 2905.21   354.3 2914.79   367.8 2919.75
#Mann= 3 ,-1,0
       0      .1       0   195.8    .045       0  213.19      .1       0
Bank Sta=195.8,213.19
XS Rating Curve= 0 ,0
Exp/Cntr(USF)=0,0
Exp/Cntr=0.3,0.1

Type RM Length L Ch R = 1 ,2938    ,58,59.6,61.4
XS GIS Cut Line= 4
2356858.87202182730729.0299934032356815.18289722730855.548170318
2356817.83234468730933.0792690412356853.02528941731061.141243047
#Sta/Elev= 30
       0 2905.39    21.3 2891.82    46.7 2881.18    63.6  2869.5    76.3 2862.28
    92.8 2849.04     106 2842.17   114.4 2839.29   131.3 2837.23   159.5 2839.07
   163.5 2836.85   167.5 2832.88   171.5 2830.38  184.44  2823.5   195.5 2822.67
   203.5 2823.54   207.5 2826.13   211.5 2827.34   219.8  2823.9   223.2 2823.97
   232.3 2826.94   240.6 2828.33   249.2 2833.56   265.6 2840.86   276.9 2848.81
   286.2 2856.99   301.3 2866.31   319.4 2881.85   327.7 2889.97   344.2 2900.45
#Mann= 3 ,-1,0
       0      .1       0  184.44    .045       0   203.5      .1       0
Bank Sta=184.44,203.5
XS Rating Curve= 0 ,0
Exp/Cntr(USF)=0,0
Exp/Cntr=0.3,0.1

Type RM Length L Ch R = 1 ,2879    ,72.4,65.6,66.1
XS GIS Cut Line= 4
 2356813.0868958730726.7407347592356764.98403938730868.804018939
2356759.48820222730931.7730568962356763.13109021731067.207276973
#Sta/Elev= 30
       0 2893.48      11 2887.85    19.5 2885.77      31 2878.47    36.4 2876.76
    43.7 2870.25    53.3 2864.39      72 2854.02    91.3 2844.83   100.4 2838.86
   112.4 2832.69   129.3 2828.07     140 2828.01   146.2 2826.58   154.4 2822.39
   162.4 2815.85  180.17 2811.42   186.5 2810.66   190.5 2811.48   194.5 2811.81
   202.6 2814.72   213.9 2815.77   238.6 2813.78   242.6  2814.4   290.6 2851.92
   298.6 2857.42   314.6 2872.46   328.2 2883.61   342.6 2893.33   348.7 2895.95
#Mann= 3 ,-1,0
       0      .1       0  180.17    .045       0   190.5      .1       0
#XS Ineff= 2 , 0
                          214.43         2826.82
Permanent Ineff=
       F       F
Bank Sta=180.17,190.5
XS Rating Curve= 0 ,0
Exp/Cntr(USF)=0,0
Exp/Cntr=0.3,0.1

Type RM Length L Ch R = 1 ,2813    ,115.8,121.6,119.9
XS GIS Cut Line= 4
2356775.83939576730716.752393149 2356693.9615655730860.043634489
2356705.66652815730923.595344649 2356719.1766908731053.714188373
#Sta/Elev= 30
       0 2886.59    28.1 2872.76    37.3 2865.16    51.2 2860.03      65 2851.88
    76.3 2847.71      88 2840.03    97.2 2836.81   108.5 2831.04   120.3 2826.35
   129.1 2821.03   147.9  2818.5   152.5 2817.22   167.9 2805.08   174.3  2801.9
   178.2 2801.01   182.5 2800.52   195.4 2801.03   206.9 2802.66   218.5 2802.38
   231.2 2804.89   247.3 2806.49   255.4  2810.9   267.4 2815.14   283.5 2824.84
   295.6 2833.79   315.7  2850.2   335.8 2864.18   343.8 2871.37   360.5 2881.84
#Mann= 3 ,-1,0
       0      .1       0   178.2    .045       0   195.4      .1       0
Bank Sta=178.2,195.4
XS Rating Curve= 0 ,0
Exp/Cntr=0.3,0.1

Type RM Length L Ch R = 1 ,2691    ,83.9,85.3,81.6
XS GIS Cut Line= 4
2356605.44184035730680.9114355862356581.67262179730786.266890858
2356593.23602541730905.7553950072356596.44808198 731013.68049553
#Sta/Elev= 30
       0 2853.06     8.5 2846.76      29 2829.13    45.4 2816.96    64.9 2809.75
    74.1    2804    78.2  2802.1    94.6 2796.43     123 2790.45     127 2790.03
   142.3  2790.4   153.3 2792.52   167.2 2793.74   175.3  2791.7   184.1 2787.66
  196.36 2784.51   203.4 2783.41   207.4 2784.48   215.4 2786.78   223.5  2786.6
   231.5 2787.57   243.5 2791.77   251.5 2795.38   259.5 2801.23   271.5 2807.44
   287.5 2818.58   299.5 2828.21   315.5 2839.93   327.5 2844.28     336 2849.25
#Mann= 3 ,-1,0
       0      .1       0  196.36    .045       0   207.4      .1       0
#XS Ineff= 2 , 0
                          219.69          2791.9
Permanent Ineff=
       F       F
Bank Sta=196.36,207.4
XS Rating Curve= 0 ,0
Exp/Cntr(USF)=0,0
Exp/Cntr=0.3,0.1

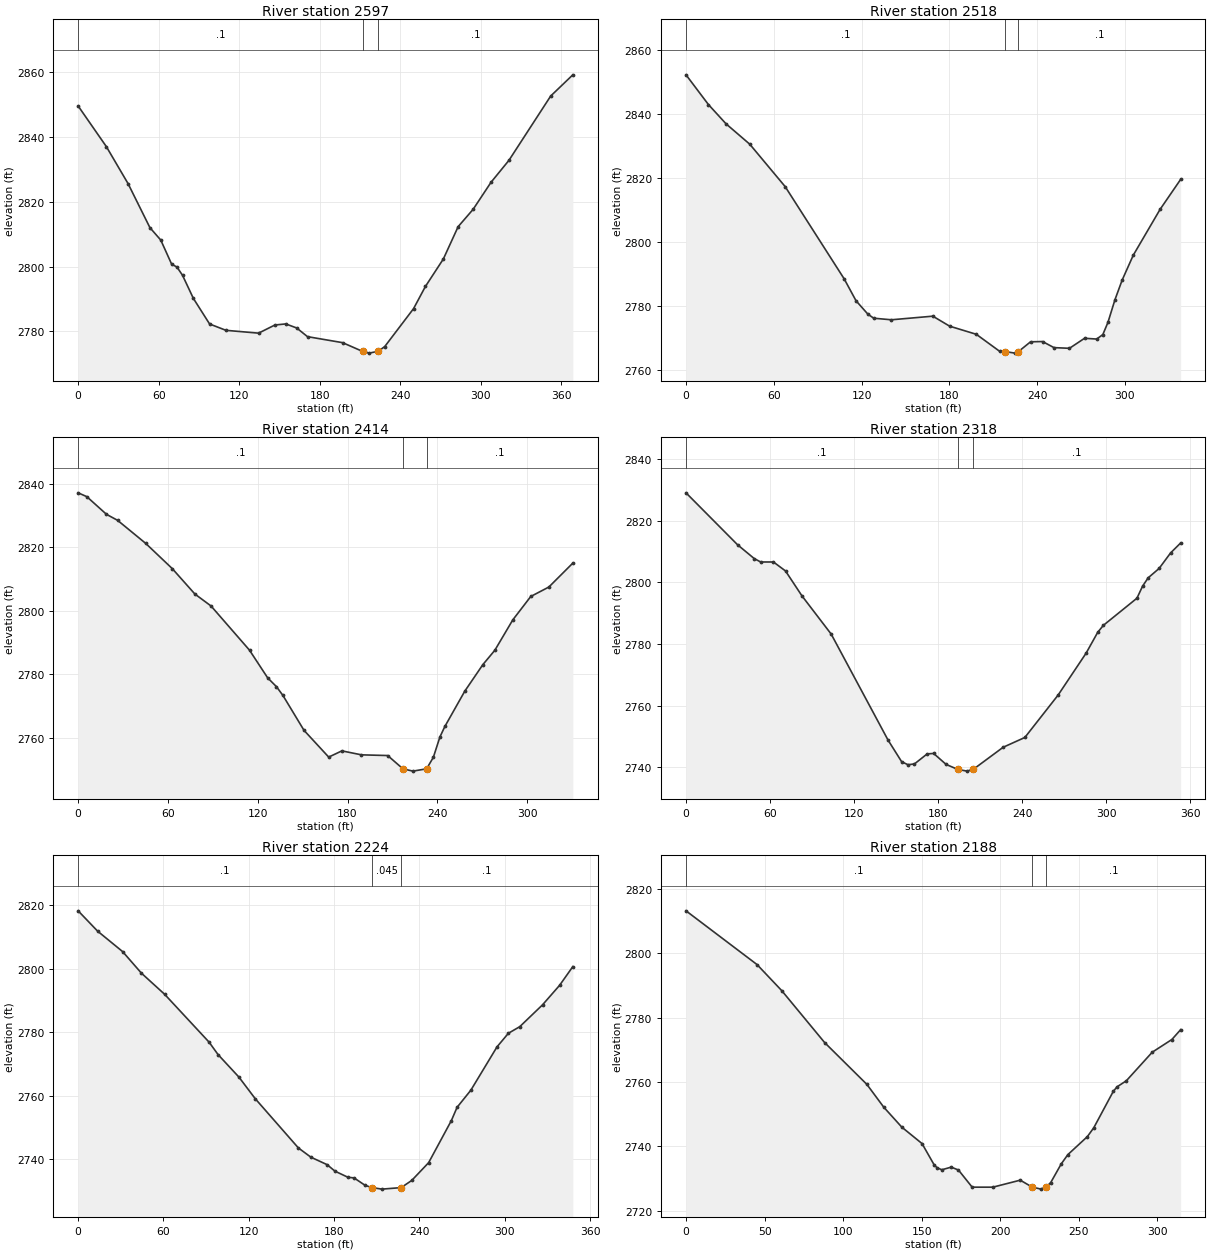
Type RM Length L Ch R = 1 ,2597    ,66.4,71.6,76.8
XS GIS Cut Line= 4
2356540.11241053730688.4381467512356510.64490184730867.186803192
 2356524.5874502730922.6140424112356581.41741157731040.033904314
#Sta/Elev= 30
       0 2849.42      21 2836.93    37.2 2825.53    53.5 2811.97    61.6 2808.14
    69.7 2800.73    73.7 2799.82    77.8 2797.31    85.9 2790.19      98 2782.31
   110.2 2780.36   134.5 2779.49   146.7    2782   154.8 2782.33   162.9 2781.09
     171 2778.41   197.2 2776.56  212.01 2773.88     217 2773.34   223.82773.926
   228.6 2775.37   250.1 2787.06   258.9 2793.86   272.3 2802.34   283.3 2812.27
   294.5 2817.62   307.8 2825.92   321.2  2832.7   352.3 2852.48   368.8 2859.01
#Mann= 3 ,0,0
       0      .1       0  212.01    .045       0   223.8      .1       0
Bank Sta=212.01,223.8
XS Rating Curve= 0 ,0
Exp/Cntr(USF)=0,0
Exp/Cntr=0.3,0.1

Type RM Length L Ch R = 1 ,2518    ,109.9,111.5,109.3
XS GIS Cut Line= 4
2356510.32531428730669.9859857772356487.23897375730844.011389493
2356424.35222059730915.9436212032356405.82252319730980.329695359
#Sta/Elev= 30
       0 2852.22    15.3 2842.94    27.4 2836.89    43.6 2830.53    67.8 2817.27
   108.1 2788.46   116.2 2781.62   124.3 2777.43   128.3 2776.16   140.4 2775.67
   168.7  2776.8   180.2 2773.67   198.4 2771.14   214.3 2765.84   218.2 2765.72
   224.9 2765.25  227.15 2765.71   235.5 2768.79   243.7 2768.87   251.5 2766.97
   262.1 2766.76   272.4 2769.89   280.7 2769.65   284.9 2771.05   288.4 2774.88
   293.2 2781.97   298.1 2788.08   305.7 2795.86     324 2810.16   338.1 2819.56
#Mann= 3 ,-1,0
       0      .1       0   218.2    .045       0  227.15      .1       0
Bank Sta=218.2,227.15
XS Rating Curve= 0 ,0
Exp/Cntr(USF)=0,0
Exp/Cntr=0.3,0.1

Type RM Length L Ch R = 1 ,2414    ,103.3,103.8,105.2
XS GIS Cut Line= 3
2356449.74615117730667.8973190532356349.64956923730895.655023883
2356343.78394537730977.111424218
#Sta/Elev= 30
       0 2837.07     5.8 2835.86    18.9 2830.31    26.4 2828.39    45.1 2821.16
    62.9 2813.19      78 2805.19    88.8 2801.42   114.5  2787.5   126.6  2778.8
   132.5 2776.01   136.8 2773.26   150.9 2762.26   167.4 2753.83   176.2 2755.79
   189.3 2754.54   206.8 2754.32  217.05 2750.12   223.7 2749.41   232.8 2750.14
   237.3 2753.74   241.7 2760.16     245 2763.47   258.3 2774.58   270.4 2782.96
   278.4 2787.48   290.4 2797.05   302.4 2804.42   314.5  2807.4   330.5 2814.93
#Mann= 3 ,-1,0
       0      .1       0  217.05    .045       0   232.8      .1       0
Bank Sta=217.05,232.8
XS Rating Curve= 0 ,0
Exp/Cntr(USF)=0,0
Exp/Cntr=0.3,0.1

Type RM Length L Ch R = 1 ,2318    ,92.8,94,97.6
XS GIS Cut Line= 3
2356369.97127306730642.534373418 2356264.6226082730833.060283153
 2356264.4195458730968.376607037
#Sta/Elev= 30
       0 2829.03    36.8 2812.17    48.7 2807.69    53.3 2806.59    62.4 2806.59
      71 2803.68    82.7 2795.62   103.6 2783.19   144.2 2748.78   153.9 2741.77
   158.4 2740.81     163 2741.06   172.1 2744.32   176.7 2744.47   185.6 2740.91
   193.8 2739.31   200.5 2738.73  204.94 2739.29   226.3 2746.47   241.8 2749.65
   265.5 2763.39   285.5    2777   293.8 2783.77   297.8 2786.02   321.8 2794.84
   325.8 2798.74   329.8 2801.45   337.6 2804.49   345.8 2809.53     353 2812.77
#Mann= 3 ,-1,0
       0      .1       0   193.8    .045       0  204.94      .1       0
Bank Sta=193.8,204.94
XS Rating Curve= 0 ,0
Exp/Cntr(USF)=0,0
Exp/Cntr=0.3,0.1

Type RM Length L Ch R = 1 ,2224    ,40.8,36.1,34.5
XS GIS Cut Line= 4
2356316.36242245730646.6910523432356201.74497972730782.823330604
2356175.62162372730835.1753577852356181.91365348 730946.45451233
#Sta/Elev= 30
       0 2818.24    13.7 2811.84    31.3  2805.4    44.5 2798.62    60.8 2791.98
    92.1  2776.9    98.4 2772.99   113.1 2765.89   124.5 2759.13   154.9  2743.6
   163.7 2740.69   175.1 2738.34   180.6  2736.3   189.8 2734.36     194 2734.18
   201.8 2731.84   206.5 2731.13   213.7 2730.64  227.19 2731.12   234.6 2733.37
   246.5 2738.97   262.5 2752.23   266.5 2756.39   276.2 2761.79   294.6 2775.43
   302.6  2779.7   310.6 2781.78   326.6 2788.65   338.6 2794.79   347.9 2800.68
#Mann= 3 ,-1,0
       0      .1       0   206.5    .045       0  227.19      .1       0
Bank Sta=206.5,227.19
XS Rating Curve= 0 ,0
Exp/Cntr=0.3,0.1

Type RM Length L Ch R = 1 ,2188    ,129.5,123.8,119.3
XS GIS Cut Line= 4
2356284.44635256730639.516265996 2356170.9308251730766.070739181
2356144.22069554730826.6685761522356124.14401986730902.596170859
#Sta/Elev= 30
       0 2813.11    45.2 2796.43    60.9 2788.35    88.2 2772.23   115.1 2759.24
   125.8 2752.19   137.3 2745.98   150.2 2740.87   158.1  2734.1     160 2733.32
   162.8 2732.74   168.8 2733.56   173.4 2732.65   182.1 2727.34   195.3 2727.34
   212.7 2729.51  220.14  2727.4   225.9 2726.73   229.1 2727.38   232.1 2728.77
   238.8 2734.57     243 2737.44   255.4 2743.02   259.5 2745.78   271.9 2757.06
   274.3 2758.48   280.2 2760.35   296.7 2769.23   309.2 2773.17   314.8 2776.24
#Mann= 3 ,-1,0
       0      .1       0  220.14    .045       0   229.1      .1       0
Bank Sta=220.14,229.1
XS Rating Curve= 0 ,0
Exp/Cntr(USF)=0,0
Exp/Cntr=0.3,0.1

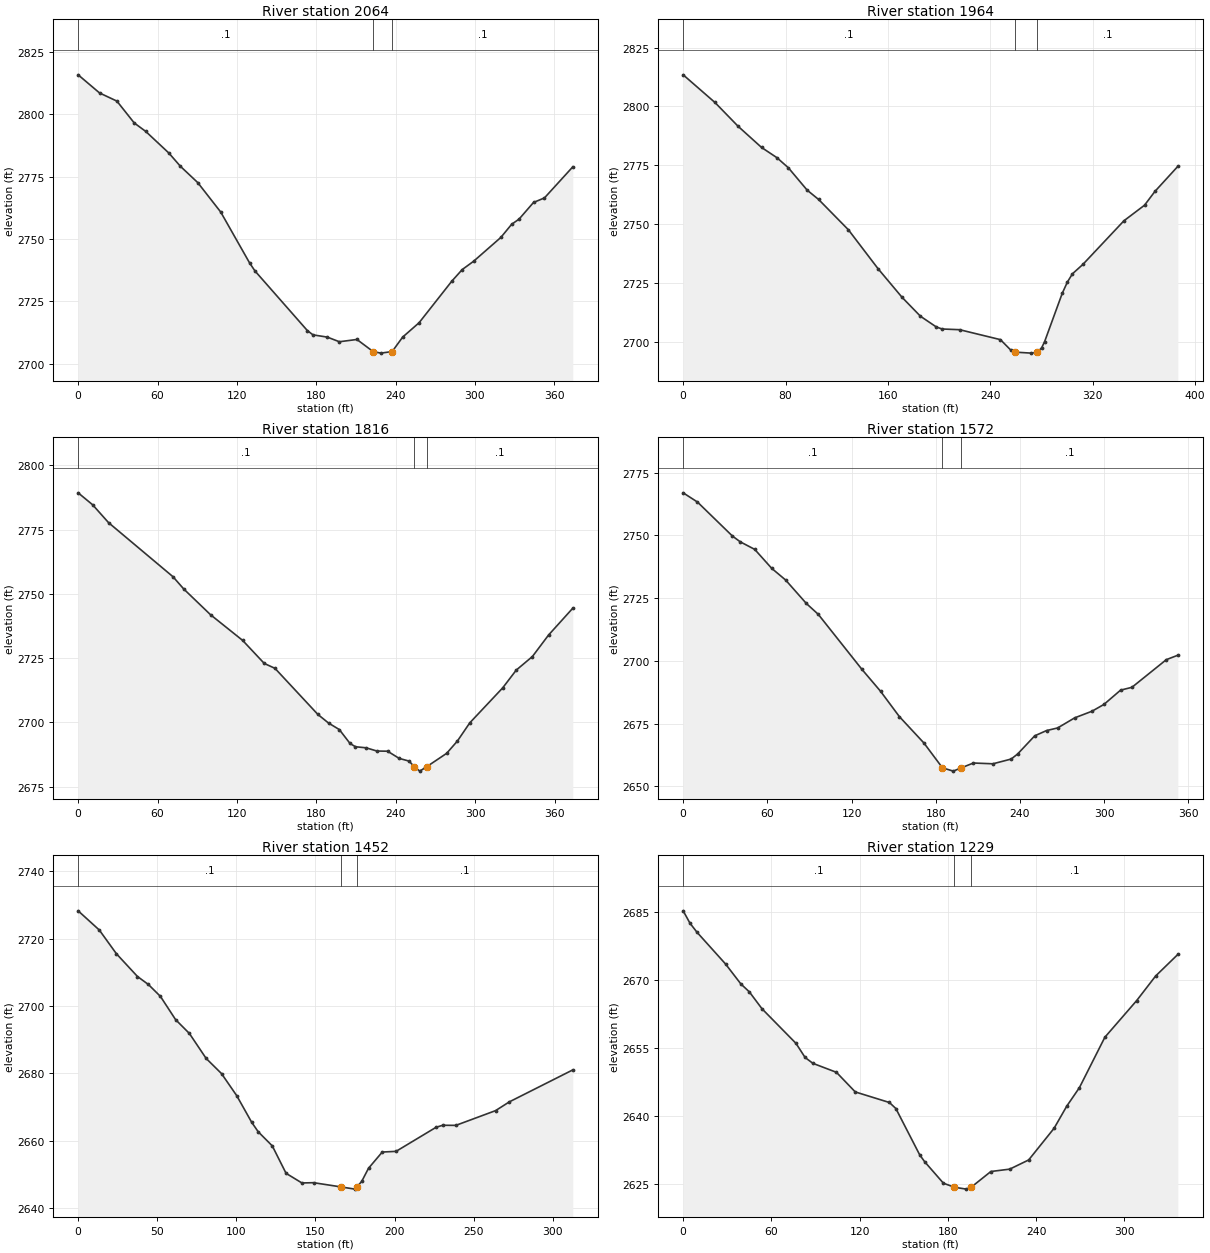
Type RM Length L Ch R = 1 ,2064    ,98.1,99.5,100.3
XS GIS Cut Line= 4
2356129.20434794730558.2830067032356045.17589012730751.564176329
2356054.51100774730788.7315969482356084.59518667730909.969418727
#Sta/Elev= 30
       0 2815.79    16.2 2808.52    29.3 2805.26    42.4 2796.51    51.1 2793.12
    68.6 2784.45    77.3 2779.15    90.4 2772.63   107.8 2760.82   129.6 2740.46
   133.7 2737.21   173.3 2713.33   177.6  2711.6   188.4 2710.71   197.5 2708.85
   210.8 2709.76   223.1 2704.89   228.9 2704.29  237.43 2704.92   245.4 2710.73
   257.8 2716.47   282.5  2733.1   290.4 2737.77     299 2741.09   319.6 2750.64
   327.8 2755.92   333.4 2757.99   344.3 2764.65   352.6 2766.48     374 2778.92
#Mann= 3 ,-1,0
       0      .1       0   223.1    .045       0  237.43      .1       0
Bank Sta=223.1,237.43
XS Rating Curve= 0 ,0
Exp/Cntr(USF)=0,0
Exp/Cntr=0.3,0.1

Type RM Length L Ch R = 1 ,1964    ,143.2,147.9,149
XS GIS Cut Line= 4
2356069.78682496730543.3729746822355950.93776529 730762.14770771
2355954.72370837730804.6720421592355964.26400203730899.054657491
#Sta/Elev= 30
       0 2813.46    24.8 2801.72      43 2791.54    61.2 2782.61    73.3 2778.22
    82.2 2773.94    96.9 2764.43   105.8 2760.49   129.1 2747.59   152.3 2731.03
     171  2718.9   185.4 2710.84   197.8 2706.28   202.3 2705.42     216 2705.12
   247.9 2700.89     256 2696.44  259.32 2695.58   272.1 2695.16   276.7 2695.56
   280.1 2697.42   282.4 2700.02   296.2 2720.59   300.2 2725.36   304.2  2728.9
   312.3 2732.86   344.4 2751.42   360.5 2758.04   368.6 2763.89   386.5 2774.54
#Mann= 3 ,-1,0
       0      .1       0  259.32    .045       0   276.7      .1       0
Bank Sta=259.32,276.7
XS Rating Curve= 0 ,0
Exp/Cntr(USF)=0,0
Exp/Cntr=0.3,0.1

Type RM Length L Ch R = 1 ,1816    ,240.3,244.7,246.6
XS GIS Cut Line= 2
 2355859.9098204730490.4664257672355799.63419107730859.258105234
#Sta/Elev= 30
       0 2789.33    10.9  2784.7      23 2777.71    71.7 2756.66    79.8  2751.9
     100  2741.9   124.3 2731.89   140.6 2722.94   148.7 2721.03   181.1  2703.1
   189.2 2699.73   197.3 2697.21   205.4  2691.8   209.5 2690.52   217.6  2690.1
   225.7 2688.85   233.8 2688.78   242.5    2686     250 2684.93     254 2682.74
   258.1 2681.03   263.4 2682.77   278.4 2687.95   286.5 2692.72   295.9 2699.83
   320.7  2713.4     331 2720.35   343.2 2725.63   355.4 2733.99   373.7 2744.43
#Mann= 3 ,-1,0
       0      .1       0     254    .045       0   263.4      .1       0
Bank Sta=254,263.4
XS Rating Curve= 0 ,0
Exp/Cntr(USF)=0,0
Exp/Cntr=0.3,0.1

Type RM Length L Ch R = 1 ,1572    ,127.2,119.8,114.3
XS GIS Cut Line= 4
2355781.18627328730501.9985292362355698.16575237730583.606199454
2355617.31517334730668.6819211112355594.27550741730785.267331942
#Sta/Elev= 30
       0 2766.94    10.2 2763.26    35.1 2749.73    40.7 2747.42      51 2744.42
    63.1 2736.87      73 2732.23    87.8 2722.88    96.3 2718.55   127.4 2696.65
   140.7 2687.91   154.1 2677.83   171.6 2667.32   184.8 2657.44   192.5 2656.11
   198.2 2657.41   206.9 2659.34   220.8 2659.03   233.8 2660.92   238.4 2662.93
   250.6 2670.17     259 2672.26   266.9  2673.3   279.1 2677.33   291.4 2679.96
   299.9 2682.66   311.8 2688.36   319.9 2689.49   344.4  2700.5   352.6 2702.26
#Mann= 3 ,-1,0
       0      .1       0   184.8    .045       0   198.2      .1       0
Bank Sta=184.8,198.2
XS Rating Curve= 0 ,0
Exp/Cntr(USF)=0,0
Exp/Cntr=0.3,0.1

Type RM Length L Ch R = 1 ,1452    ,217.1,223.1,223.7
XS GIS Cut Line= 4
2355578.73575135730462.1089014592355518.09188579 730551.98981004
2355555.82397854 730641.24361418 2355524.4466828730743.805222652
#Sta/Elev= 30
       0 2728.22    13.4 2722.51    24.2 2715.48    37.5 2708.74    44.4 2706.37
      52 2702.84    61.6 2695.94    70.3 2691.85    80.9 2684.44    90.6 2679.95
   100.2 2673.41   109.7 2665.48   113.8 2662.69   122.7  2658.5   131.4 2650.37
   141.4 2647.51   148.8 2647.59   166.2 2646.33   174.9 2645.68  176.16 2646.32
   179.2 2647.97   183.5 2651.86   192.2 2656.68   200.9 2656.88   226.2 2664.02
   230.4 2664.62   238.7 2664.59   263.8 2668.96   272.5 2671.56   312.6 2681.04
#Mann= 3 ,-1,0
       0      .1       0   166.2    .045       0  176.16      .1       0
Bank Sta=166.2,176.16
XS Rating Curve= 0 ,0
Exp/Cntr(USF)=0,0
Exp/Cntr=0.3,0.1

Type RM Length L Ch R = 1 ,1229    ,96.9,97.9,98.5
XS GIS Cut Line= 4
2355422.91422121 730473.379432082355342.62596698730590.990843897
2355332.91323471730660.4083127292355379.43992863730775.188855203
#Sta/Elev= 30
       0 2685.33     4.6 2682.61     9.4  2680.6    28.8  2673.6    39.2  2669.2
      45 2667.44    53.6 2663.71    76.7 2656.08    82.9 2652.96    88.2 2651.67
   104.2 2649.69     117 2645.36   140.2 2643.03   144.6  2641.7   160.8 2631.48
   164.2 2629.95   176.9 2625.23   184.4 2624.32   192.6 2623.91  195.76 2624.32
   209.2  2627.8     222 2628.32   234.9 2630.35   252.2 2637.35   260.8 2642.23
   269.4 2646.31   286.7 2657.43   308.3 2665.51   321.2 2670.94   336.3  2675.7
#Mann= 3 ,-1,0
       0      .1       0   184.4    .045       0  195.76      .1       0
Bank Sta=184.4,195.76
XS Rating Curve= 0 ,0
Exp/Cntr(USF)=0,0
Exp/Cntr=0.3,0.1