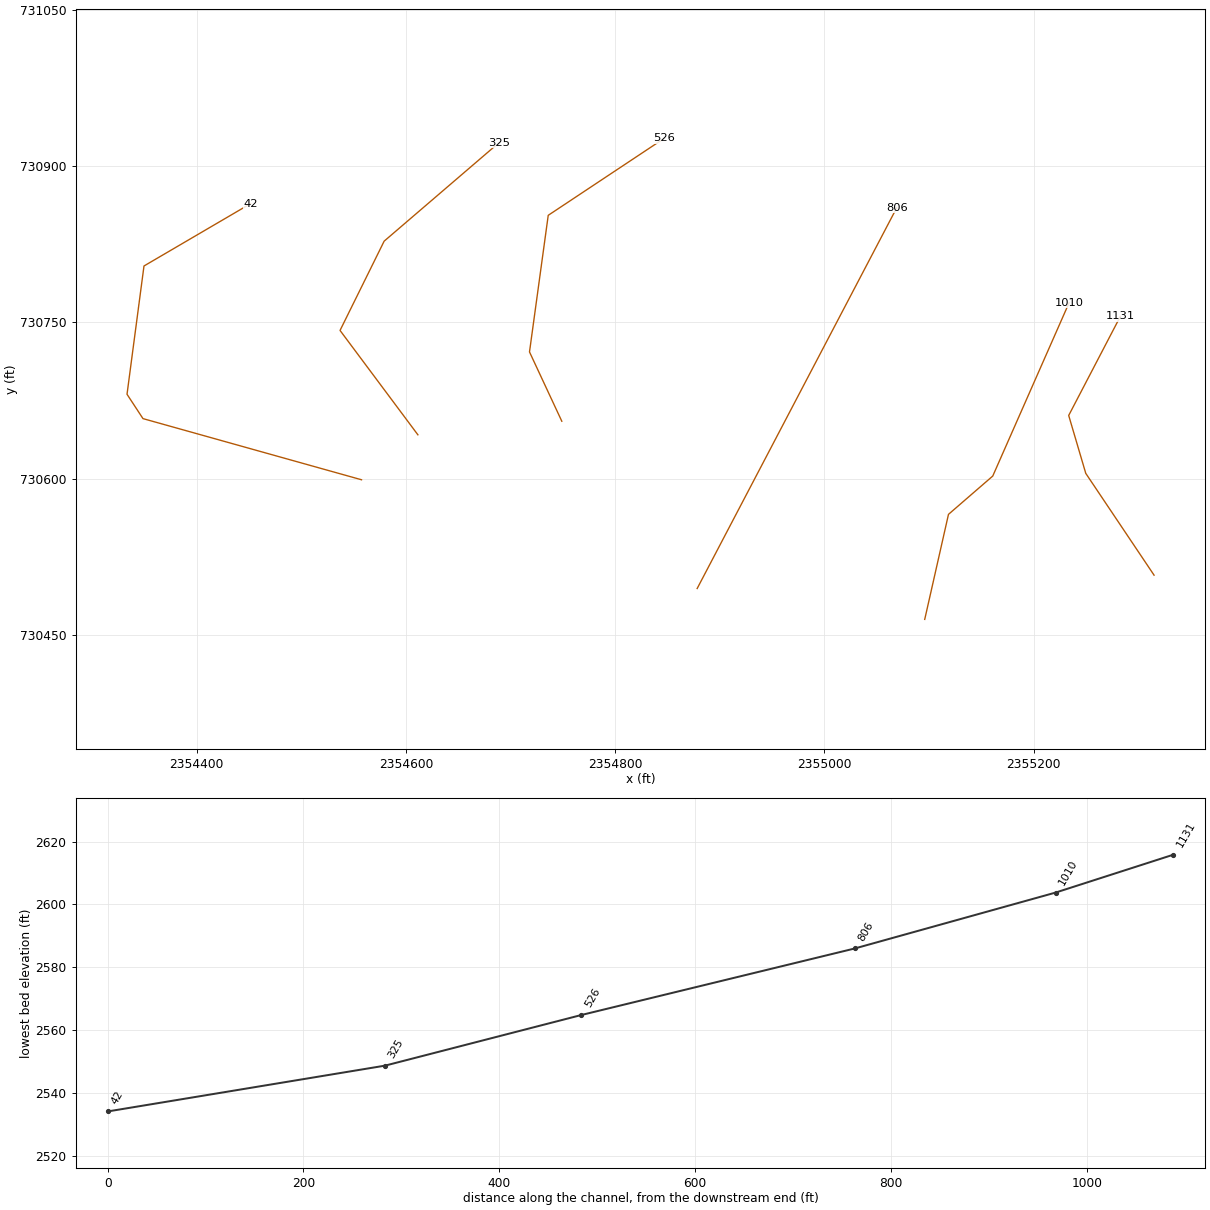
HEC-RAS study PSSNCMPRN.prj: PSSNCMPRN

--- PSSNCMPRN.g01 (geometry) --- (continued)

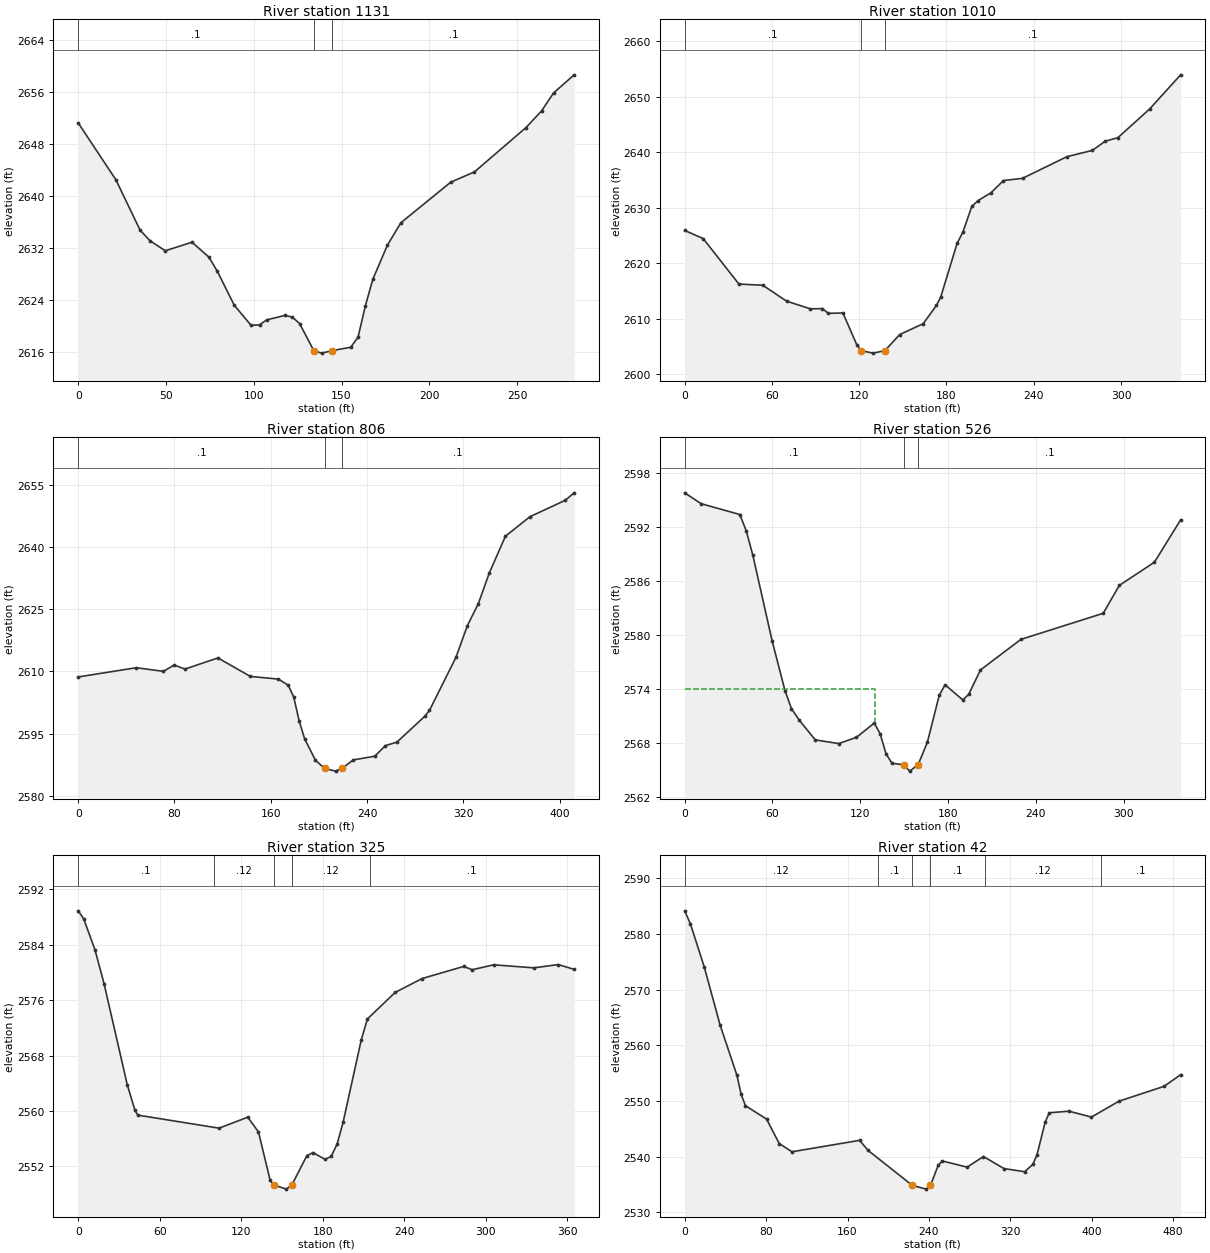
Type RM Length L Ch R = 1 ,1131    ,129.2,120.4,111.2
XS GIS Cut Line= 4
2355315.11146418730507.2625373332355249.84292645730604.935455765
 2355233.5201093730660.516786691 2355282.8737348730755.561003257
#Sta/Elev= 30
       0 2651.24    21.5 2642.47    35.2 2634.77    40.8 2633.13    49.6 2631.57
    64.8 2632.89    74.5 2630.58    79.3 2628.39    88.9 2623.19    98.5 2620.09
   103.3 2620.18   107.3 2620.94   117.7 2621.63   121.9 2621.38   126.1 2620.38
  134.18 2616.22   138.6 2615.83   144.8 2616.22   155.2 2616.73   159.4 2618.28
   163.6 2623.13   167.8 2627.17   176.1 2632.42   183.8 2635.88   212.2 2642.12
   225.7  2643.7     255  2650.5   263.9 2653.07   270.8 2655.85   282.5 2658.63
#Mann= 3 ,-1,0
       0      .1       0  134.18    .045       0   144.8      .1       0
Bank Sta=134.18,144.8
XS Rating Curve= 0 ,0
Exp/Cntr(USF)=0,0
Exp/Cntr=0.3,0.1

Type RM Length L Ch R = 1 ,1010    ,200.5,204.8,206.6
XS GIS Cut Line= 4
2355095.91364503730464.8170366922355118.62045328730565.612436577
2355160.94245326730602.3805540742355233.90545209730768.676297124
#Sta/Elev= 30
       0 2625.89    12.7 2624.43    37.3 2616.22    53.7 2616.01    70.1 2613.14
    86.5 2611.75    94.7  2611.8    98.8 2610.94   108.8 2611.01   118.3  2605.3
   121.3 2604.21   129.6 2603.77  137.69 2604.22   147.8 2607.11     164 2609.08
   173.1 2612.36   176.1 2613.92   187.3 2623.55   191.3 2625.59   197.4 2630.21
   201.8 2631.29   210.5 2632.66   219.2 2634.89   232.3 2635.29   262.9  2639.2
   280.4 2640.33   289.1 2641.97   297.9 2642.63   319.7 2647.79     341 2653.95
#Mann= 3 ,-1,0
       0      .1       0   121.3    .045       0  137.69      .1       0
Bank Sta=121.3,137.69
XS Rating Curve= 0 ,0
Exp/Cntr(USF)=0,0
Exp/Cntr=0.3,0.1

Type RM Length L Ch R = 1 ,806     ,277.9,279.5,281.3
XS GIS Cut Line= 2
2354878.42444281730494.4560254382355069.14783322730859.785336653
#Sta/Elev= 30
       0 2608.69    48.2  2610.9    70.8 2610.04    79.8 2611.54    88.8 2610.59
   116.1 2613.26     143 2608.82   166.4 2608.16   174.5  2606.7   179.1 2603.83
   183.6 2598.11   188.1 2593.83   197.1 2588.64   204.8 2586.67   213.8 2586.02
   219.4 2586.72   228.6 2588.72   246.4 2589.61   255.3 2592.16   264.8 2592.99
   287.9 2599.19   291.9 2600.65   313.9 2613.42   323.4 2621.05   332.5 2626.34
   341.5 2633.65     355 2642.56   375.4 2647.26   404.7  2651.2   412.1    2653
#Mann= 3 ,-1,0
       0      .1       0   204.8    .045       0   219.4      .1       0
Bank Sta=204.8,219.4
XS Rating Curve= 0 ,0
Exp/Cntr(USF)=0,0
Exp/Cntr=0.3,0.1

Type RM Length L Ch R = 1 ,526     ,200.1,200.6,193.9
XS GIS Cut Line= 4
2354749.05038241730654.9656127792354718.16812461730721.466839582
2354736.06806881730852.5718363132354847.04670831730926.531823746
#Sta/Elev= 30
       0 2595.75    11.3 2594.54    37.7 2593.34    42.1 2591.52    46.5 2588.88
    59.8 2579.29    68.6 2573.76      73 2571.78    78.4 2570.48    89.3 2568.31
   105.3  2567.9   117.4 2568.59   129.6 2570.18   133.6 2568.99   137.6 2566.78
   141.7 2565.71   149.7 2565.55   153.8 2564.84   159.6 2565.56   165.9 2568.05
     174 2573.26     178 2574.43   190.1 2572.75   194.1 2573.36   202.2 2576.08
   229.8 2579.47   286.1 2582.37   297.1 2585.47   321.1 2588.04     339 2592.75
#Mann= 3 ,-1,0
       0      .1       0   149.7    .045       0   159.6      .1       0
#XS Ineff= 2 , 0
          129.89 2573.96
Permanent Ineff=
       F       F
Bank Sta=149.7,159.6
XS Rating Curve= 0 ,0
Exp/Cntr(USF)=0,0
Exp/Cntr=0.3,0.1

Type RM Length L Ch R = 1 ,325     ,280,283.3,293.5
XS GIS Cut Line= 4
2354611.49576658 730641.949604552354537.08834318730742.105718841
2354579.24408114730827.7752411912354689.05714902730922.308385773
#Sta/Elev= 30
       0  2588.9       4 2587.76    12.3  2583.3      19 2578.41    36.1  2563.8
    41.8 2560.09    43.9 2559.41   103.7 2557.53   124.8 2559.11   132.7 2556.99
   141.3    2550  143.86 2549.33   153.3 2548.73  157.28 2549.33   168.3 2553.55
   172.8 2554.01   181.7 2553.03   186.2 2553.44   190.6 2555.24     195 2558.37
   208.4 2570.29   212.9 2573.29   233.3 2577.12   253.1 2579.12   283.7 2580.87
   290.1  2580.4   305.9 2581.11   335.4 2580.67   353.4 2581.14   365.1 2580.45
#Mann= 5 ,-1,0
       0      .1       0     100     .12       0  143.86    .045       0
  157.28     .12       0  214.77      .1       0
Bank Sta=143.86,157.28
XS Rating Curve= 0 ,0
Exp/Cntr(USF)=0,0
Exp/Cntr=0.3,0.1

Type RM Length L Ch R = 1 ,42      ,,,
XS GIS Cut Line= 5
2354557.63492495730598.8019458252354348.74033983730657.485609727
2354333.48343267730680.8533796632354349.70182547 730803.94861183
2354451.69115884730863.853701886
#Sta/Elev= 30
       0 2584.18     5.7 2581.81    19.3 2574.04    34.8 2563.65    51.4 2554.59
    55.5 2551.18    59.7 2549.16    80.5 2546.74    92.9 2542.35   105.4 2540.87
   171.9 2542.93   180.2 2541.12  223.75 2534.82   237.4 2534.16   241.5 2534.82
   249.3 2538.53   253.3 2539.22   277.5 2538.11   293.6 2540.02   313.8 2537.85
     334 2537.29     342 2538.59   346.1 2540.28   354.2 2546.18   358.2 2547.88
   377.6 2548.17   399.7 2547.11   426.8 2549.97   471.1 2552.64   487.3 2554.73
#Mann= 6 ,-1,0
       0     .12       0     190      .1       0  223.75    .045       0
   241.5      .1       0  294.89     .12       0  409.05      .1       0
Bank Sta=223.75,241.5
XS Rating Curve= 0 ,0
Exp/Cntr(USF)=0,0
Exp/Cntr=0.3,0.1
LCMann Table=0

Chan Stop Cuts=-1
Use User Specified Reach Order=0
Composite Channel Slope=5